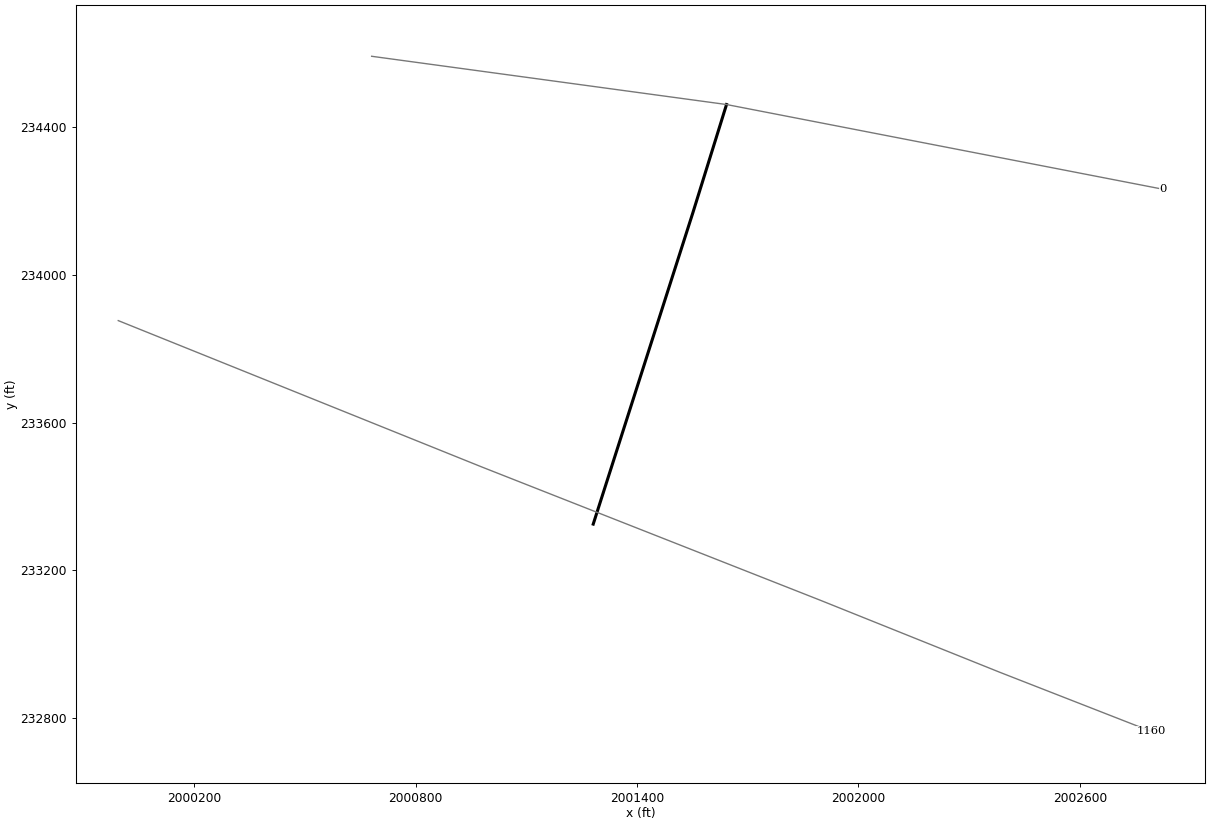
--- NEWRV_A.prj (project) ---

Proj Title=NEWRV_A
Current Plan=p01
Default Exp/Contr=0,0
English Units
Geom File=g01
Flow File=f01
Plan File=p01
Background Map Layer=QC
BEGIN DESCRIPTION:
Stream Name: New River
Flood Zone: Approximate
Summers County, West Virginia
HEC-RAS Version: 5.0.7
Hydrology Method:
Gage Weighting.
Model Notes:
END DESCRIPTION:
DSS File=dss
DSS Export Rating Curves= 0
DSS Export Rating Curve Sorted= 0
DSS Export Volume Flow Curves= 0
DXF OffsetX= 0
DXF OffsetY= 0
DXF ScaleX= 0
DXF ScaleY= 0

--- NEWRV_A.p01 (plan) ---

Plan Title=Floodplain
Program Version=5.07
Short Identifier=Floodplain
Geom File=g01
Flow File=f01
Subcritical Flow
K Sum by GR= 0
Std Step Tol= 0.01
Critical Tol= 0.01
Num of Std Step Trials= 20
Max Error Tol= 0.3
Flow Tol Ratio= 0.001
Split Flow NTrial= 30
Split Flow Tol= 0.02
Split Flow Ratio= 0.02
Log Output Level= 0
Friction Slope Method= 1
Unsteady Friction Slope Method= 2
Unsteady Bridges Friction Slope Method= 1
Parabolic Critical Depth
Global Vel Dist= 0 , 0 , 0
Global Log Level= 0
CheckData=True
Encroach Param=-1 ,0,0, 0
Computation Interval=0.1SEC
Output Interval=1MIN
Instantaneous Interval=Max Profile
Mapping Interval=1HOUR
Computation Time Step Use Courant=        0
Computation Time Step Use Time Series=    0
Computation Time Step Count To Double=0
Computation Time Step Max Doubling=0
Computation Time Step Max Halving=0
Computation Time Step Residence Courant=0
Run HTab= 0
Run UNet= 0
Run Sediment= 0
Run PostProcess= 0
Run WQNet= 0
Run RASMapper= 0
UNET Theta= 0
UNET Theta Warmup= 0
UNET ZTol= 0
UNET ZSATol= 0
UNET MxIter= 0
UNET Max Iter WO Improvement= 0
UNET MaxInSteps= 0
UNET DtIC= 0
UNET DtMin= 0
UNET MaxCRTS= 0
UNET WFStab= 0
UNET SFStab= 0
UNET WFX= 1
UNET SFX= 1
UNET 1D Methodology=Finite Difference
UNET DSS MLevel= 1
UNET Pardiso=0
UNET DZMax Abort= 0
UNET Use Existing IB Tables= 0
UNET Froude Reduction=False
UNET Froude Limit= 0
UNET Froude Power= 0
UNET D1 Cores= 0
UNET D2 Coriolis=0
UNET D2 Cores= 0
UNET D2 Theta= 1
UNET D2 Theta Warmup= 1
UNET D2 Z Tol= 0.01
UNET D2 Volume Tol= 0.01
UNET D2 Max Iterations= 20
UNET D2 Equation= 0
UNET D2 RampUpFraction=0.1
UNET D2 TimeSlices= 1
UNET D2 Eddy Viscosity=0.3
UNET D2 BCVolumeCheck=0
UNET D1D2 MaxIter= 0
UNET D1D2 ZTol=0.01
UNET D1D2 QTol=0.1
UNET D1D2 MinQTol=1
DSS File=dss
Write IC File= 0
Write IC File at Fixed DateTime=0
Write IC File at Sim End=0
Echo Input=False
Echo Parameters=False
Echo Output=False
Write Detailed= 0
HDF Write Warmup=0
HDF Write Time Slices=0
HDF Flush=0
HDF Face Node Velocities=0
HDF Compression= 1
HDF Chunk Size= 1
HDF Spatial Parts= 1
HDF Use Max Rows=0
HDF Fixed Rows= 1
Calibration Method= 0
Calibration Iterations= 20
Calibration Max Change=0.05
Calibration Tolerance=0.2
Calibration Maximum=1.5
Calibration Minimum=0.5
Calibration Optimization Method= 1
WQ AD Non Conservative
WQ ULTIMATE=-1
WQ Max Comp Step=1HOUR
WQ Output Interval=15MIN
WQ Output Selected Increments= 0
WQ Output face flow=0
WQ Output face velocity=0
WQ Output face area=0
WQ Output face dispersion=0
WQ Output cell volume=0
WQ Output cell surface area=0
WQ Output cell continuity=0
WQ Output cumulative cell continuity=0
WQ Output face conc=0
WQ Output face dconc_dx=0
WQ Output face courant=0
WQ Output face peclet=0
WQ Output face adv mass=0
WQ Output face disp mass=0
WQ Output cell mass=0
WQ Output cell source sink temp=0
WQ Output nsm pathways=0
WQ Output nsm derived pathways=0
WQ Output MaxMinRange=-1
WQ Daily Max Min Mean=-1
WQ Daily Range=0
WQ Daily Time=0
WQ Create Restart=0
WQ Fixed Restart=0
WQ System Summary=0
WQ Write To DSS=0
WQ Use Fixed Temperature=0
Sorting and Armoring Iterations= 10
XS Update Threshold= 0.02
Bed Roughness Predictor= 0
Hydraulics Update Threshold= 0.02
Energy Slope Method= 1
Volume Change Method= 1
Sediment Retention Method= 0
XS Weighting Method= 0
Number of US Weighted Cross Sections= 1
Number of DS Weighted Cross Sections= 1
Upstream XS Weight=0
Main XS Weight=1
Downstream XS Weight=0
Number of DS XS's Weighted with US Boundary= 1
Upstream Boundary Weight= 1
Weight of XSs Associated with US Boundary= 0
Number of US XS's Weighted with DS Boundary= 1
Downstream Boundary Weight= 0.5
Weight of XSs Associated with DS Boundary= 0.5
Percentile Method= 0
Sediment Output Level= 3
Mass or Volume Output= 0
Output Increment Type= 1
Profile and TS Output Increment= 1
XS Output Flag= 0
XS Output Increment= 10
Write Gradation File= 0
Read Gradation Hotstart= 0
Write HDF5 File= 1
Write Binary Output= 1
Write DSS Sediment File= 0
SV Curve= 0
Specific Gage Flag= 0

--- NEWRV_A.f01 (steady flow) ---

Flow Title=Flow
Program Version=5.07
Number of Profiles= 6
Profile Names=01pct,10pct,04pct,02pct,0_2pct,01plus
River Rch & RM=NEWRV_A,Main            ,1160
   65551   51191   57057   61333  285334   73541
Boundary for River Rch & Prof#=NEWRV_A,Main            , 1
Up Type= 0
Dn Type= 1
Dn Known WS=1376.4
Boundary for River Rch & Prof#=NEWRV_A,Main            , 2
Up Type= 0
Dn Type= 1
Dn Known WS=1375
Boundary for River Rch & Prof#=NEWRV_A,Main            , 3
Up Type= 0
Dn Type= 1
Dn Known WS=1375.6
Boundary for River Rch & Prof#=NEWRV_A,Main            , 4
Up Type= 0
Dn Type= 1
Dn Known WS=1376
Boundary for River Rch & Prof#=NEWRV_A,Main            , 5
Up Type= 0
Dn Type= 1
Dn Known WS=1394.2
Boundary for River Rch & Prof#=NEWRV_A,Main            , 6
Up Type= 0
Dn Type= 1
Dn Known WS=1377
DSS Import GetInterval= 0
DSS Import GetPeak= 0
DSS Import FillOption= 0

--- NEWRV_A.g01 (geometry) ---

Geom Title=Geometry
Program Version=5.07

River Reach=NEWRV_A         ,Main
Reach XY= 3
2001281.22725246233324.970756831     2001551.389      234169.133
     2001642.484      234462.036

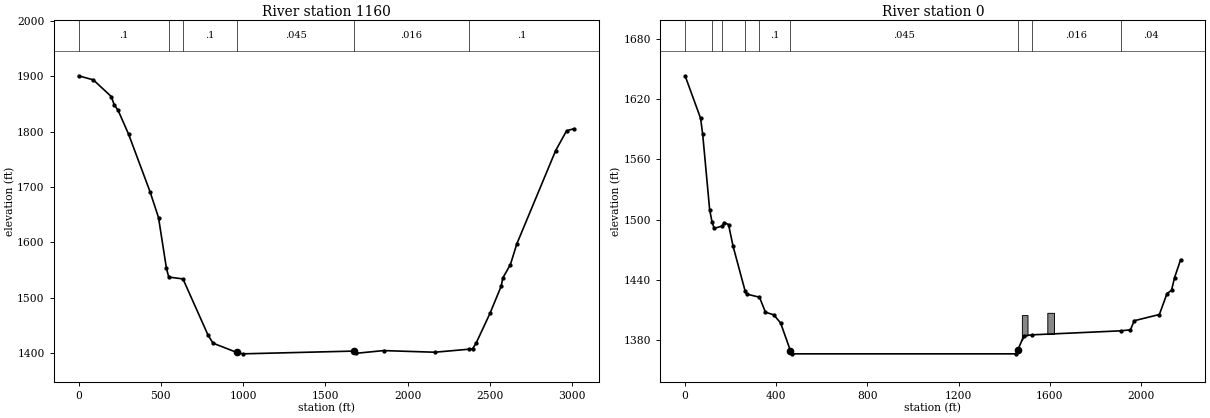
Type RM Length L Ch R = 1 ,1160    ,1031.2,1159.6,1297.1
XS GIS Cut Line= 5
1999994.07275559233876.4502891132000979.03925846233479.905333413
2001896.84895431233118.5377528152002382.93631936232923.463218156
2002792.27304783232763.566058599
#Sta/Elev= 30
       0 1900.52    89.5  1893.1   198.6 1863.03   215.5 1848.65     240 1838.14
   303.5 1795.28   434.6 1690.92   485.4 1644.91   533.6 1553.35   547.7  1537.6
   634.1 1534.26   785.4 1433.62   816.5 1418.42   961.9 1401.64   997.2 1399.19
  1674.1 1404.16  1685.1 1400.16  1853.9 1405.04  2164.5  1402.1  2369.5 1407.47
  2394.3 1408.34  2415.2 1418.33  2500.3 1472.46  2567.5 1520.95  2578.1 1536.24
  2623.9 1560.11  2662.6 1597.27  2899.1  1765.8  2965.5 1801.45  3011.4 1805.14
#Mann= 6 ,-1 , 0
       0      .1       0   547.7    .016       0   634.1      .1       0
   961.9    .045       0  1674.1    .016       0  2369.5      .1       0
Bank Sta=961.9,1674.1
XS Rating Curve= 0 ,0
Exp/Cntr(USF)=0,0
Exp/Cntr=0.3,0.1

Type RM Length L Ch R = 1 ,0       ,0,0,0
XS GIS Cut Line= 3
     2000680.775      234592.795     2001642.484      234462.036
     2002824.873      234232.552
#Sta/Elev= 30
       0 1643.32    68.1 1600.93    77.3 1584.87   107.8 1509.82   118.1 1497.88
   127.7 1491.33   164.1 1493.76   170.7  1497.2   190.6  1495.2   210.5 1473.65
   263.4 1429.01   270.1  1425.9   326.3 1422.81   352.8 1407.86   389.2 1405.25
   419.1 1397.19     462  1369.7   468.7  1366.4    1453  1366.4  1459.9    1370
  1486.7 1384.32  1520.6 1385.31  1912.5 1389.32  1954.6 1390.32  1971.4 1399.38
  2081.6 1405.57    2115 1426.35    2135 1429.69  2148.4 1442.39    2175 1460.19
#Mann= 9 ,-1 , 0
       0      .1       0   118.1    .016       0   164.1      .1       0
   263.4    .016       0   326.3      .1       0     462    .045       0
  1459.9     .04       0  1520.6    .016       0  1912.5     .04       0
#Block Obstruct= 2 ,-1
 1478.13 1502.89 1404.97 1589.81 1619.27 1407.24
Bank Sta=462,1459.9
XS Rating Curve= 0 ,0
Exp/Cntr(USF)=0,0
Exp/Cntr=0.3,0.1
LCMann Table=0

Chan Stop Cuts=-1
Use User Specified Reach Order=0
Composite Channel Slope=5